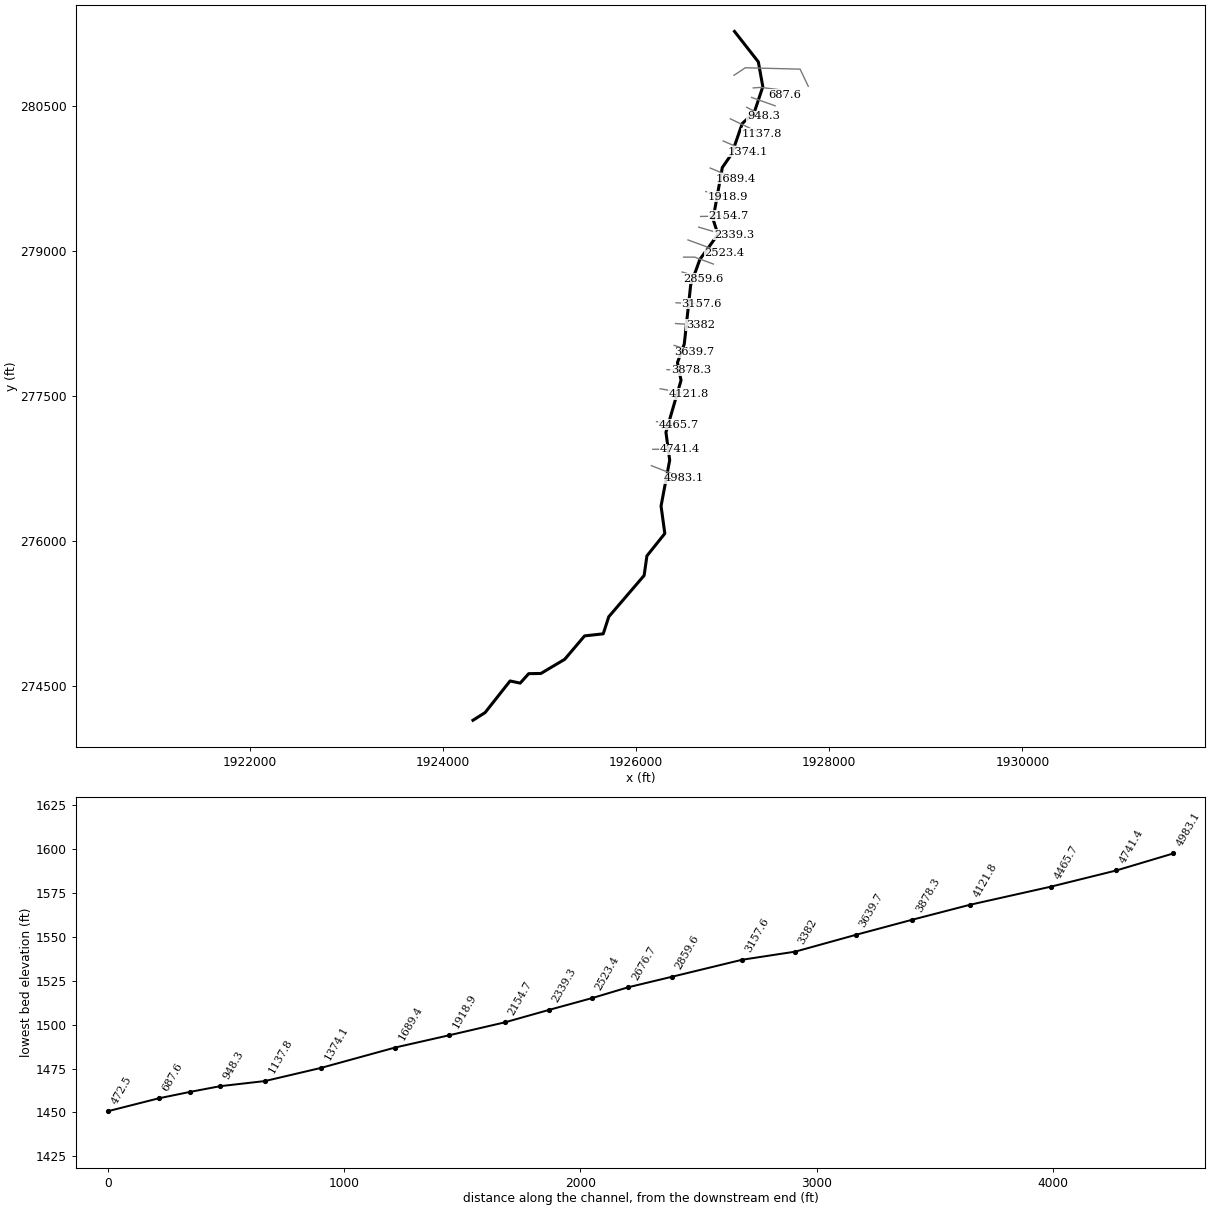
--- PANTHERRN.prj (project) ---

Proj Title=PANTHERRN
Current Plan=p01
Default Exp/Contr=0,0
English Units
Geom File=g01
Flow File=f01
Plan File=p01
BEGIN DESCRIPTION:
END DESCRIPTION:
DSS Export Rating Curves= 0
DSS Export Rating Curve Sorted= 0
DSS Export Volume Flow Curves= 0
DXF OffsetX= 0
DXF OffsetY= 0
DXF ScaleX= 0
DXF ScaleY= 0

--- PANTHERRN.p01 (plan) ---

Plan Title=Floodplain
Program Version=4.00
Geom File=g01
Flow File=f01
K Sum by GR=0
Std Step Tol=0.01
Critical Tol=0.01
Num of Std Step Trials=20
Max Error Tol=0.3
Flow Tol Ratio=0.001
Split Flow NTrial=30
Split Flow Tol=0.02
Split Flow Ratio=0.02
Log Output Level=0
Friction Slope Method=1
Unsteady Friction Slope Method=2
Unsteady Bridges Friction Slope Method=1
Global Log Level=0
CheckData=False
Run HTab=0
Run UNet=0
Run PostProcess=0
UNET Theta=0
UNET Theta Warmup=0
UNET ZTol=0
UNET ZSATol=0
UNET MxIter=0
UNET MaxInSteps=0
UNET DtIC=0
UNET DtMin=0
UNET MaxCRTS=0
UNET WFStab=0
UNET SFStab=0
UNET WFX=0
UNET SFX=0
UNET DSS MLevel=0
UNET DZMax Abort=0
UNET Convert EG Bridges=0
UNET Use Existing IB Tables=0
UNET Froude Limit=0
UNET Froude Power=0
Write IC File=0
Echo Input=False
Echo Output=False
Write Detailed=0

--- PANTHERRN.f01 (steady flow) ---

Flow Title=NFF Regression Equation
Program Version=4.10
Number of Profiles= 1
Profile Names=P100yr
River Rch & RM=PANTHERRN,Main            ,4983.1
734.7564
River Rch & RM=PANTHERRN,Main            ,1918.9
800.2431
River Rch & RM=PANTHERRN,Main            ,472.5
830.8898
Boundary for River Rch & Prof#=PANTHERRN,Main            , 1
Up Type= 0
Dn Type= 3
Dn Slope=0.03139
DSS Import GetInterval= 0
DSS Import GetPeak= 0
DSS Import FillOption= 0

--- PANTHERRN.g01 (geometry) ---

Geom Title=USGS 10m DEM
Program Version=4.10

River Reach=PANTHERRN       ,Main
Reach XY= 30
     1924310.412      274140.526     1924436.396      274220.518
     1924694.729      274547.601      1924799.59      274525.379
     1924887.784      274623.295     1925014.173      274625.379
     1925260.701      274771.906     1925466.358      275014.485
       1925659.5      275035.752     1925716.792      275212.835
     1926083.021      275640.075     1926111.757      275843.044
     1926297.174      276074.554     1926258.285      276359.276
     1926347.697      276833.961     1926308.804      277122.473
     1926465.186      277660.874     1926427.972      277844.471
     1926498.687      278036.769     1926565.236      278650.293
     1926660.289      278913.314     1926847.268      279171.647
     1926796.486      279330.501     1926892.584      279864.184
     1926990.699      280006.325     1927098.878      280319.539
     1927223.318      280435.747     1927312.061      280700.978
     1927265.707       280958.27     1927018.861      281273.678

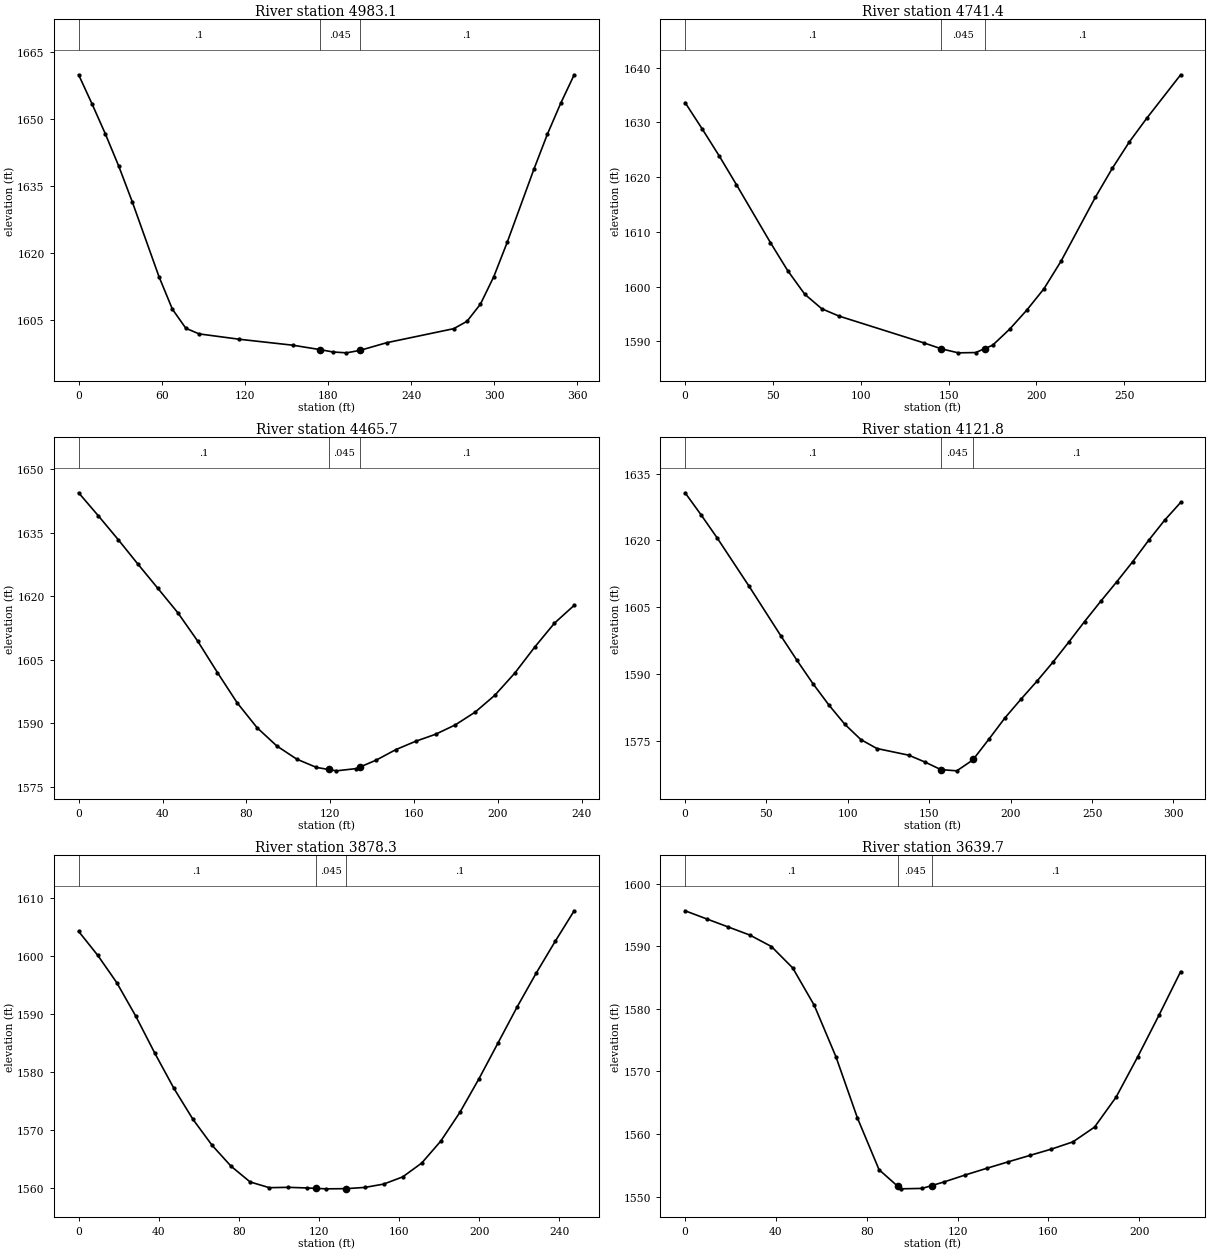
Type RM Length L Ch R = 1 ,4983.1  ,232.1,241.8,250.7
XS GIS Cut Line= 2
     1926157.757       276777.16     1926491.114      276647.255
#Sta/Elev= 25
       0    1660     9.7 1653.45    19.3 1646.73      29 1639.47    38.7 1631.52
      58 1614.72    67.7  1607.4    77.4 1603.13      87 1601.86     116 1600.66
   154.7 1599.32     174 1598.35   183.7  1597.8   193.4 1597.61   203.1 1598.16
   222.4 1599.88   270.8 1603.03   280.4 1604.68   290.1 1608.53   299.8 1614.73
   309.4 1622.37   328.8 1638.87   338.4 1646.62   348.1 1653.62   357.8 1659.99
#Mann= 3 , 0 , 0
       0      .1       0     174    .045       0   203.1      .1       0
Bank Sta=174,203.1
XS Rating Curve= 0 ,0
Exp/Cntr=0.3,0.1

Type RM Length L Ch R = 1 ,4741.4  ,278.8,275.7,272.5
XS GIS Cut Line= 2
     1926172.611      276946.563     1926454.729      276948.733
#Sta/Elev= 24
       0 1633.64     9.7 1628.84    19.5 1623.85    29.2 1618.64    48.6 1608.03
    58.4 1602.92    68.1 1598.61    77.8 1595.95    87.6 1594.61   136.2 1589.68
   145.9 1588.62   155.5 1587.89   165.4 1587.94   170.5 1588.65   175.1 1589.29
   184.8 1592.23   194.6 1595.73   204.3 1599.61     214 1604.64   233.5  1616.3
   243.2 1621.62   252.9 1626.45   262.7 1630.73   282.1 1638.72
#Mann= 3 , 0 , 0
       0      .1       0   145.9    .045       0   170.5      .1       0
Bank Sta=145.9,170.5
XS Rating Curve= 0 ,0
Exp/Cntr=0.3,0.1

Type RM Length L Ch R = 1 ,4465.7  ,345.2,343.9,342.4
XS GIS Cut Line= 2
     1926211.674      277233.021     1926446.049      277202.639
#Sta/Elev= 28
       0 1644.39     9.4 1638.95    18.9 1633.31    28.4 1627.46    37.8  1621.8
    47.3 1616.05    56.7 1609.41    66.2 1601.92    75.6 1594.77    85.1 1588.89
    94.5 1584.58     104 1581.47   113.4 1579.51   119.2 1579.02   122.9  1578.7
   132.4 1579.23   134.2 1579.61   141.8 1581.21   151.3 1583.72   160.7 1585.68
   170.2 1587.34   179.6 1589.55   189.1 1592.58   198.5 1596.57     208  1601.8
   217.4 1607.88   226.9 1613.59   236.3  1617.8
#Mann= 3 , 0 , 0
       0      .1       0   119.2    .045       0   134.2      .1       0
Bank Sta=119.2,134.2
XS Rating Curve= 0 ,0
Exp/Cntr=0.3,0.1

Type RM Length L Ch R = 1 ,4121.8  ,242.5,243.5,244.5
XS GIS Cut Line= 2
     1926248.566      277573.733     1926548.045      277519.479
#Sta/Elev= 30
       0 1630.69     9.8 1625.75    19.6 1620.62    39.3 1609.73    58.9 1598.56
    68.7 1593.13    78.5  1587.9    88.4 1583.06    98.2 1578.74     108 1575.33
   117.8 1573.34   137.4 1571.84   147.3 1570.31   157.1 1568.61   166.9 1568.33
   176.7 1570.76   177.1 1570.95   186.5 1575.37   196.4 1580.17   206.2 1584.35
     216 1588.38   225.8 1592.63   235.6 1597.16   245.4 1601.82   255.3 1606.35
   265.1  1610.7   274.9 1615.21   284.7    1620   294.5 1624.51   304.4 1628.52
#Mann= 3 , 0 , 0
       0      .1       0   157.1    .045       0   177.1      .1       0
Bank Sta=157.1,177.1
XS Rating Curve= 0 ,0
Exp/Cntr=0.3,0.1

Type RM Length L Ch R = 1 ,3878.3  ,243.2,238.6,233.8
XS GIS Cut Line= 2
     1926320.181      277771.215     1926567.576      277766.875
#Sta/Elev= 29
       0 1604.22     9.5 1600.11      19  1595.4    28.6 1589.56    38.1 1583.18
    47.6 1577.14    57.1 1571.81    66.6 1567.36    76.1 1563.74    85.6 1561.03
    95.2 1560.04   104.7  1560.1   114.2 1559.99   118.4 1559.92   123.7 1559.84
   133.2 1559.87   133.4 1559.87   142.8 1560.08   152.3 1560.66   161.8  1561.9
   171.3 1564.29   180.8 1568.07   190.3    1573   199.8 1578.77   209.4    1585
   218.9 1591.18   228.4    1597   237.9 1602.49   247.4 1607.77
#Mann= 3 , 0 , 0
       0      .1       0   118.4    .045       0   133.4      .1       0
Bank Sta=118.4,133.4
XS Rating Curve= 0 ,0
Exp/Cntr=0.3,0.1

Type RM Length L Ch R = 1 ,3639.7  ,250.6,257.7,264.4
XS GIS Cut Line= 2
     1926393.965      278022.951     1926600.129      277951.337
#Sta/Elev= 26
       0 1595.67     9.5 1594.37      19 1593.08    28.5 1591.79      38 1589.96
    47.4 1586.53    56.9 1580.54    66.4 1572.36    75.9 1562.54    85.4 1554.29
    93.6 1551.65    94.9 1551.23   104.4  1551.3   108.6 1551.75   113.9 1552.32
   123.4 1553.45   132.8 1554.51   142.3 1555.55   151.8 1556.57   161.3 1557.58
   170.8 1558.74   180.3  1561.1   189.8  1565.9   199.3 1572.33   208.8 1579.08
   218.2 1585.95
#Mann= 3 , 0 , 0
       0      .1       0    93.6    .045       0   108.6      .1       0
Bank Sta=93.6,108.6
XS Rating Curve= 0 ,0
Exp/Cntr=0.3,0.1

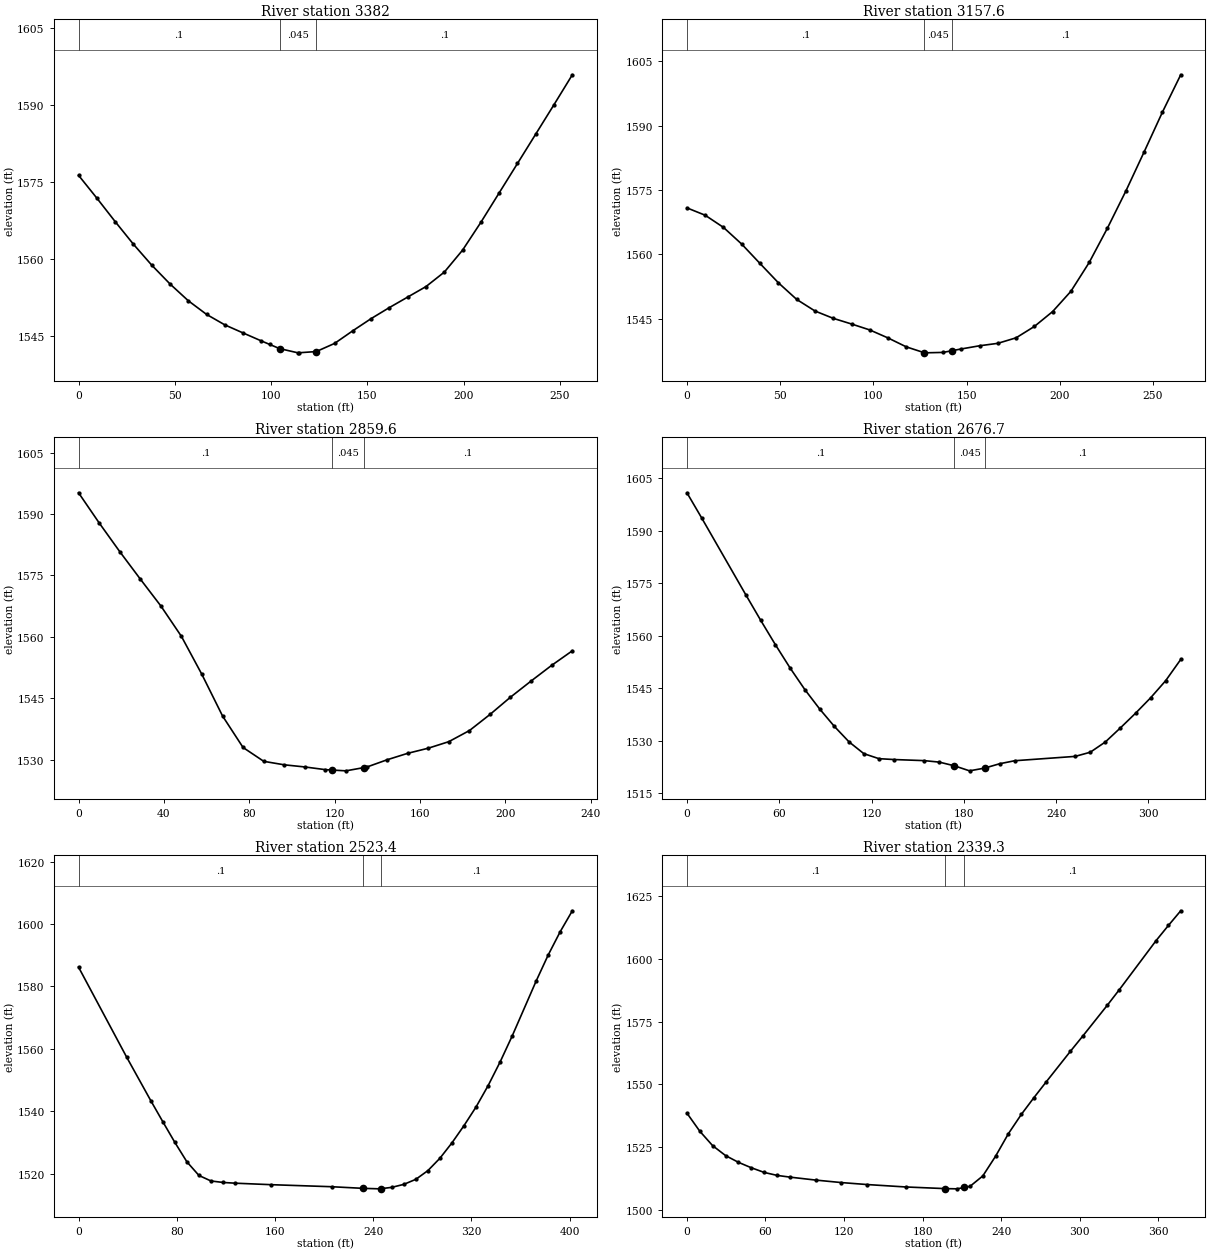
Type RM Length L Ch R = 1 ,3382    ,223.6,224.5,224.8
XS GIS Cut Line= 2
     1926409.156      278248.646     1926665.233      278233.455
#Sta/Elev= 30
       0  1576.3     9.5 1571.85      19 1567.27    28.5 1562.84      38 1558.76
    47.5 1555.08      57  1551.8    66.5 1549.13      76 1547.08    85.5  1545.5
      95 1543.94    99.3 1543.26   104.5 1542.44     114 1541.62   114.3 1541.63
   123.5 1541.87     133 1543.46   142.5 1545.94     152 1548.31   161.5 1550.47
     171 1552.52   180.5 1554.57     190 1557.39   199.5 1561.69     209 1567.12
   218.5 1572.87     228 1578.61   237.5 1584.36     247 1590.11   256.5 1595.94
#Mann= 3 , 0 , 0
       0      .1       0   104.5    .045       0   123.5      .1       0
Bank Sta=104.5,123.5
XS Rating Curve= 0 ,0
Exp/Cntr=0.3,0.1

Type RM Length L Ch R = 1 ,3157.6  ,303.6,298,292.2
XS GIS Cut Line= 2
     1926413.497       278463.49     1926678.254      278454.809
#Sta/Elev= 30
       0 1570.84     9.8 1569.12    19.6 1566.28    29.4 1562.38    39.2 1557.86
    49.1 1553.34    58.9 1549.47    68.7 1546.77    78.5 1545.06    88.3 1543.74
    98.1 1542.35   107.9 1540.48   117.7  1538.4   127.1 1537.07   127.5 1537.01
   137.4 1537.11   142.1  1537.5   147.2 1537.92     157 1538.66   166.8 1539.23
   176.6 1540.52   186.4 1543.17   196.2 1546.65     206 1551.38   215.8  1558.1
   225.6 1566.13   235.5  1574.8   245.3 1583.93   255.1  1593.2   264.9  1601.9
#Mann= 3 , 0 , 0
       0      .1       0   127.1    .045       0   142.1      .1       0
Bank Sta=127.1,142.1
XS Rating Curve= 0 ,0
Exp/Cntr=0.3,0.1

Type RM Length L Ch R = 1 ,2859.6  ,184.3,182.9,181.5
XS GIS Cut Line= 2
     1926476.431        278782.5     1926697.785      278715.226
#Sta/Elev= 27
       0 1595.17     9.6 1587.86    19.3 1580.81    28.9 1574.13    38.6 1567.52
    48.2 1560.12    57.8 1550.83    67.5 1540.66    77.1 1532.98    86.8  1529.6
    96.4 1528.75     106 1528.23   115.7 1527.57   118.9 1527.47   125.3 1527.28
   133.9 1528.09     135 1528.19   144.6 1529.98   154.2 1531.55   163.9 1532.81
   173.5  1534.4   183.2 1537.12   192.8 1541.04   202.4 1545.26   212.1 1549.22
   221.7 1553.03   231.4 1556.59
#Mann= 3 , 0 , 0
       0      .1       0   118.9    .045       0   133.9      .1       0
Bank Sta=118.9,133.9
XS Rating Curve= 0 ,0
Exp/Cntr=0.3,0.1

Type RM Length L Ch R = 1 ,2676.7  ,153.3,153.3,153.3
XS GIS Cut Line= 3
     1926491.622       278936.58     1926606.639       278936.58
     1926799.781      278864.965
#Sta/Elev= 28
       0 1600.84     9.6 1593.63    38.3 1571.66    47.9 1564.43    57.5 1557.42
    67.1 1550.74    76.7 1544.56    86.3 1539.04    95.8 1534.09   105.4 1529.64
     115 1526.28   124.8 1524.85   134.6  1524.6   154.2 1524.29   164.1 1523.86
   173.9  1522.8   183.7 1521.37   193.5 1522.15   203.3  1523.4   213.1 1524.26
   252.4  1525.5   262.2 1526.69     272 1529.62   281.8 1533.65   291.6 1537.82
   301.4 1542.23   311.2 1547.13     321  1553.2
#Mann= 3 , 0 , 0
       0      .1       0   173.9    .045       0   193.5      .1       0
Bank Sta=173.9,193.5
XS Rating Curve= 0 ,0
Exp/Cntr=0.3,0.1

Type RM Length L Ch R = 1 ,2523.4  ,183.1,184.1,185.1
XS GIS Cut Line= 2
     1926537.195      279114.531     1926914.799      278975.642
#Sta/Elev= 30
       0 1586.18    39.2 1557.36    58.9  1543.4    68.7 1536.65    78.5 1530.04
    88.3 1523.83    98.1 1519.47   107.9 1517.71   117.8 1517.23   127.6    1517
     157 1516.52   206.1 1515.87   231.6 1515.35   245.3 1515.19   246.6 1515.25
   255.1 1515.66     265 1516.62   274.8 1518.24   284.6 1521.02   294.4 1524.98
   304.2  1529.9     314 1535.41   323.8 1541.37   333.6 1548.17   343.5 1555.85
   353.3 1564.14   372.9  1581.8   382.7 1590.12   392.5 1597.59   402.3 1604.23
#Mann= 3 , 0 , 0
       0      .1       0   231.6    .045       0   246.6      .1       0
Bank Sta=231.6,246.6
XS Rating Curve= 0 ,0
Exp/Cntr=0.3,0.1

Type RM Length L Ch R = 1 ,2339.3  ,176.6,184.6,192.3
XS GIS Cut Line= 3
     1926647.872       279246.91     1926893.097      279175.295
     1927014.625      279168.785
#Sta/Elev= 30
       0 1538.54     9.8 1531.35    19.6  1525.6    29.5 1521.64    39.3 1518.96
    49.1  1516.8      59 1514.93    68.8 1513.75    78.6 1513.06    98.3 1511.88
   117.9 1510.89   137.6  1510.1     167 1509.14   196.8 1508.49   206.3 1508.39
   211.8 1508.93   216.2 1509.37     226 1513.52   235.8 1521.41   245.6 1530.39
   255.5 1538.08   264.8 1544.53   274.2 1550.83   292.9 1563.15   302.3 1569.18
     321 1581.43   330.4 1587.77   358.4 1607.26   367.8 1613.29   377.2 1619.13
#Mann= 3 , 0 , 0
       0      .1       0   196.8    .045       0   211.8      .1       0
Bank Sta=196.8,211.8
XS Rating Curve= 0 ,0
Exp/Cntr=0.3,0.1

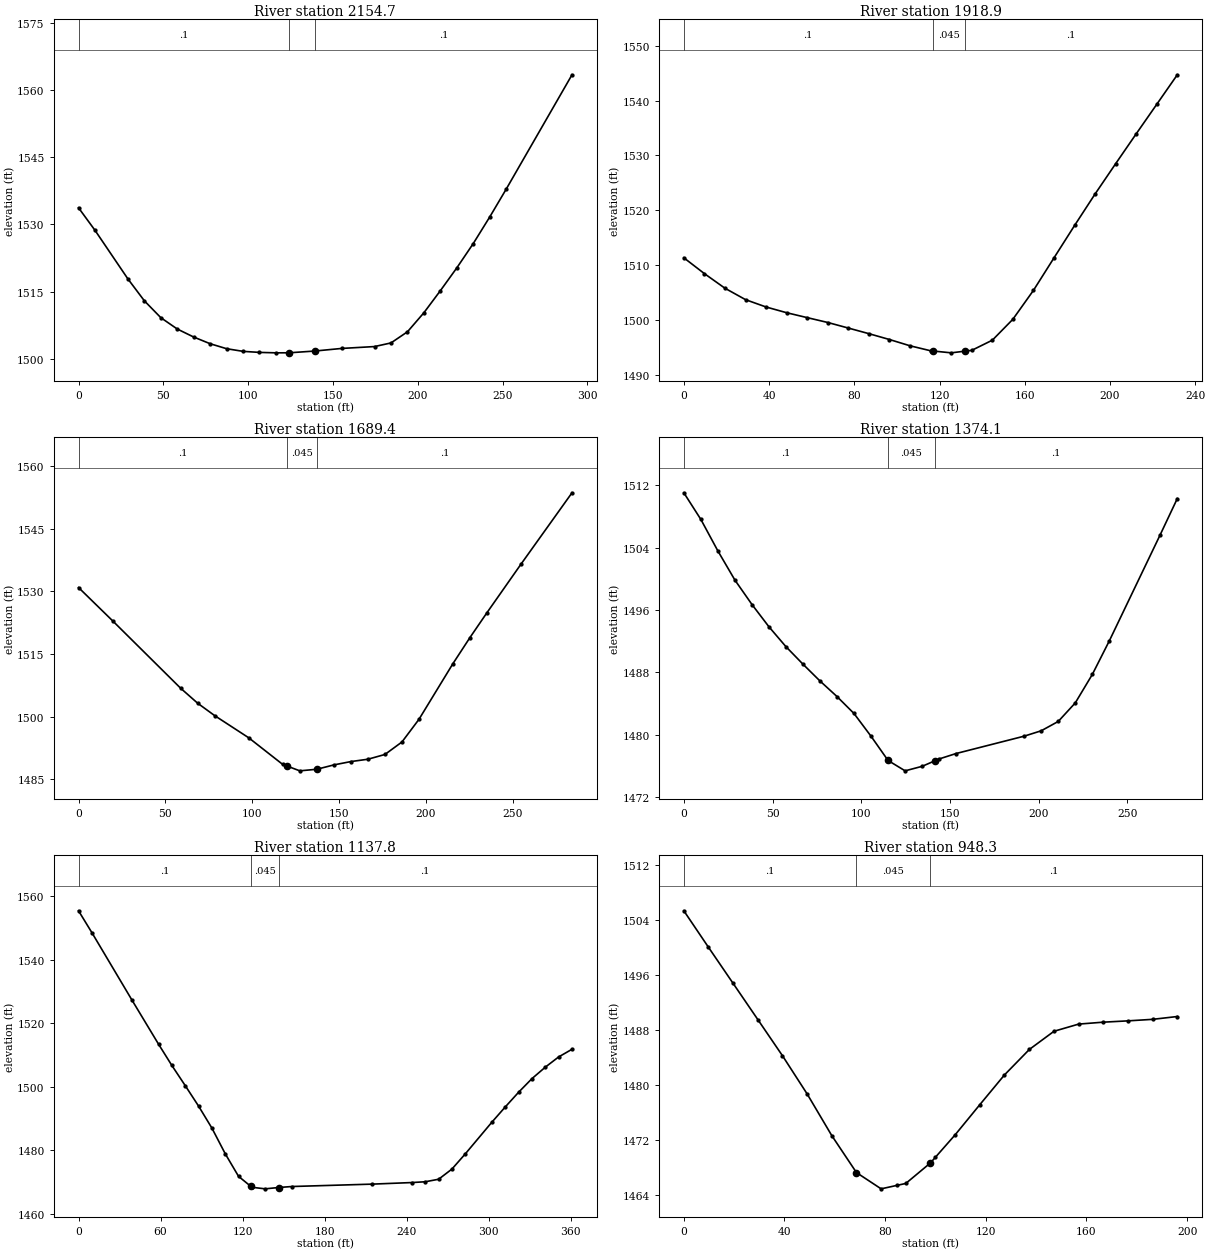
Type RM Length L Ch R = 1 ,2154.7  ,241.5,235.8,230
XS GIS Cut Line= 2
     1926667.403      279357.587     1926958.201      279364.097
#Sta/Elev= 25
       0 1533.71     9.7 1528.69    29.1 1517.86    38.8 1512.98    48.5 1509.22
    58.2 1506.69    67.9  1504.9    77.6 1503.41    87.3  1502.3      97 1501.71
   106.6 1501.48   116.4 1501.38   124.2 1501.39   139.2 1501.78   155.1 1502.36
   174.5 1502.78   184.2 1503.59   193.9 1506.07   203.6 1510.32   213.3 1515.23
     223 1520.32   232.7 1525.74   242.4 1531.66   252.1 1537.86   290.9 1563.35
#Mann= 3 , 0 , 0
       0      .1       0   124.2    .045       0   139.2      .1       0
Bank Sta=124.2,139.2
XS Rating Curve= 0 ,0
Exp/Cntr=0.3,0.1

Type RM Length L Ch R = 1 ,1918.9  ,233.3,229.4,225.8
XS GIS Cut Line= 2
     1926721.656      279615.833     1926947.351       279563.75
#Sta/Elev= 27
       0 1511.34     9.6 1508.47    19.3 1505.79      29  1503.7    38.6 1502.37
    48.3 1501.32    57.9 1500.43    67.6 1499.54    77.2 1498.53    86.9  1497.5
    96.5 1496.44   106.2 1495.29   115.8 1494.39   116.8 1494.35   125.5 1494.01
   131.8 1494.31   135.1 1494.46   144.8 1496.32   154.4 1500.12   164.1 1505.41
   173.7 1511.31   183.4 1517.24     193 1522.97   202.7 1528.52   212.3 1533.94
     222 1539.35   231.6 1544.71
#Mann= 3 , 0 , 0
       0      .1       0   116.8    .045       0   131.8      .1       0
Bank Sta=116.8,131.8
XS Rating Curve= 0 ,0
Exp/Cntr=0.3,0.1

Type RM Length L Ch R = 1 ,1689.4  ,315.6,315.4,315
XS GIS Cut Line= 2
     1926767.229      279858.889     1927029.816      279750.382
#Sta/Elev= 21
       0  1530.9    19.6 1522.94    58.8 1506.78    68.6 1503.19    78.4 1500.22
      98 1494.91   117.6 1488.52     120 1488.15   127.4    1487   137.2 1487.38
     147 1488.42   156.8 1489.22   166.6 1489.78   176.4 1490.92   186.2 1493.91
     196 1499.34   215.5 1512.64   225.3 1518.89   235.1 1524.85   254.7 1536.48
   284.1 1553.59
#Mann= 3 , 0 , 0
       0      .1       0     120    .045       0   137.2      .1       0
Bank Sta=120,137.2
XS Rating Curve= 0 ,0
Exp/Cntr=0.3,0.1

Type RM Length L Ch R = 1 ,1374.1  ,237.2,236.2,235.2
XS GIS Cut Line= 2
     1926901.778      280138.837     1927157.854       280030.33
#Sta/Elev= 26
       0 1511.03     9.6 1507.61    19.2 1503.56    28.8 1499.82    38.4 1496.69
      48 1493.82    57.5 1491.29    67.1 1489.04    76.7 1486.88    86.3 1484.88
    95.9  1482.7   105.5 1479.78   115.1 1476.67   124.7 1475.34   134.3 1475.92
   141.5 1476.63   143.8 1476.86   153.4 1477.56   191.8 1479.79   201.4 1480.48
     211 1481.68   220.6 1484.06   230.2 1487.71   239.8 1492.03   268.5 1505.66
   278.1 1510.29
#Mann= 3 , 0 , 0
       0      .1       0   115.1    .045       0   141.5      .1       0
Bank Sta=115.1,141.5
XS Rating Curve= 0 ,0
Exp/Cntr=0.3,0.1

Type RM Length L Ch R = 1 ,1137.8  ,190.6,189.5,188.4
XS GIS Cut Line= 2
     1926975.563      280368.872     1927301.083      280212.622
#Sta/Elev= 28
       0 1555.42     9.8 1548.52      39 1527.38    58.6 1513.39    68.3 1506.72
    78.1 1500.36    87.8 1493.96    97.6    1487   107.4 1478.89   117.1 1471.81
   125.9 1468.72   126.9 1468.37   136.6 1467.88   146.4  1468.3   156.1 1468.61
   214.7 1469.36     244 1469.86   253.7 1470.11   263.5  1470.9   273.2 1474.09
     283 1478.88   302.5 1488.88   312.3 1493.68     322 1498.28   331.8 1502.58
   341.6  1506.2   351.3  1509.4   361.1 1511.82
#Mann= 3 , 0 , 0
       0      .1       0   125.9    .045       0   146.4      .1       0
Bank Sta=125.9,146.4
XS Rating Curve= 0 ,0
Exp/Cntr=0.3,0.1

Type RM Length L Ch R = 1 ,948.3   ,122.8,126,129.3
XS GIS Cut Line= 2
     1927144.833      280488.229     1927318.445      280397.083
#Sta/Elev= 23
       0  1505.3     9.8    1500    19.6 1494.76    29.4 1489.52    39.2 1484.27
      49 1478.73    58.8 1472.68    68.6 1467.32    78.4 1464.96    84.9 1465.48
    88.2 1465.74      98 1468.72    99.9 1469.51   107.8 1472.79   117.6 1477.16
   127.4 1481.48   137.3 1485.18   147.1 1487.82   156.9 1488.86   166.7 1489.14
   176.5 1489.33   186.3 1489.55   196.1 1489.96
#Mann= 3 , 0 , 0
       0      .1       0    68.6    .045       0      98      .1       0
Bank Sta=68.6,98
XS Rating Curve= 0 ,0
Exp/Cntr=0.3,0.1

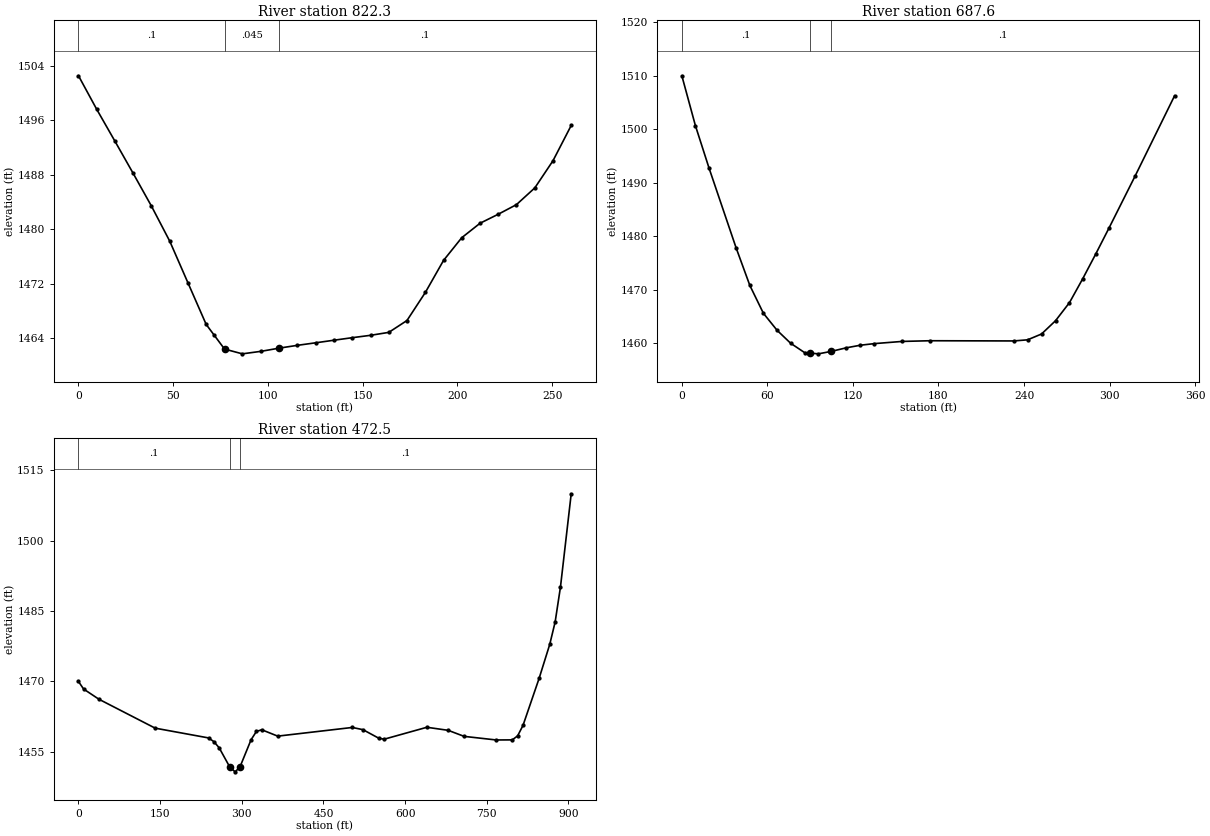
Type RM Length L Ch R = 1 ,822.3   ,129.5,134.7,139.7
XS GIS Cut Line= 2
     1927194.747      280590.226     1927439.972       280503.42
#Sta/Elev= 29
       0 1502.55     9.6 1497.64    19.3 1492.92    28.9 1488.21    38.5 1483.43
    48.2 1478.26    57.8 1472.15    67.4 1466.06    71.5 1464.53    77.1 1462.44
    86.5 1461.74    96.4 1462.11     106 1462.58   115.6 1462.99   125.2 1463.36
   134.9 1463.74   144.5 1464.11   154.2 1464.46   163.8 1464.89   173.4 1466.63
   183.1 1470.75   192.7 1475.45   202.3 1478.78     212 1480.91   221.6 1482.23
   231.2 1483.64   240.9  1486.1   250.5 1490.09   260.1 1495.26
#Mann= 3 , 0 , 0
       0      .1       0    77.1    .045       0     106      .1       0
Bank Sta=77.1,106
XS Rating Curve= 0 ,0
Exp/Cntr=0.3,0.1

Type RM Length L Ch R = 1 ,687.6   ,212.9,215.1,217.2
XS GIS Cut Line= 4
     1927213.146      280688.629     1927289.229      280694.217
     1927483.375      280670.521     1927533.288      280616.267
#Sta/Elev= 27
       0    1510     9.5 1500.69    19.1 1492.72    38.1  1477.8    47.7  1470.8
    57.2  1465.6    66.8 1462.42    76.3    1460    86.1 1458.25    89.8 1458.16
    95.8 1458.02   104.8 1458.48   115.4 1459.15   125.2 1459.63     135 1459.93
   154.5 1460.34   174.1 1460.47   232.8 1460.43   242.5 1460.64   252.3 1461.73
   262.1 1464.21   271.9  1467.6   281.1 1472.02   290.3 1476.68   299.5 1481.48
     318  1491.3   345.6 1506.26
#Mann= 3 , 0 , 0
       0      .1       0    89.8    .045       0   104.8      .1       0
Bank Sta=89.8,104.8
XS Rating Curve= 0 ,0
Exp/Cntr=0.3,0.1

Type RM Length L Ch R = 1 ,472.5   ,454.5,472.5,490.2
XS GIS Cut Line= 4
     1927013.609      280819.479     1927130.976      280897.476
     1927698.219      280883.195     1927782.494       280705.57
#Sta/Elev= 30
       0 1469.96     9.4 1468.35    37.6 1466.17   140.9    1460   238.8 1457.92
   248.5 1457.14   258.3 1455.83   277.9  1451.7   287.7 1450.68   296.5  1451.7
     317 1457.53   326.8  1459.3   336.6 1459.66   365.9  1458.3   502.9 1460.15
   522.5 1459.68   551.8 1457.84   561.6 1457.65   639.9 1460.19     679 1459.54
   708.3 1458.25   767.3 1457.48   796.8  1457.5   806.6 1458.36   816.5  1460.6
     846 1470.61   865.6 1477.89   875.5 1482.67   885.3 1490.15     905 1510.02
#Mann= 3 , 0 , 0
       0      .1       0   277.9    .045       0   296.5      .1       0
Bank Sta=277.9,296.5
XS Rating Curve= 0 ,0
Exp/Cntr=0.3,0.1

Chan Stop Cuts=-1
Use User Specified Reach Order=0
Composite Channel Slope=5